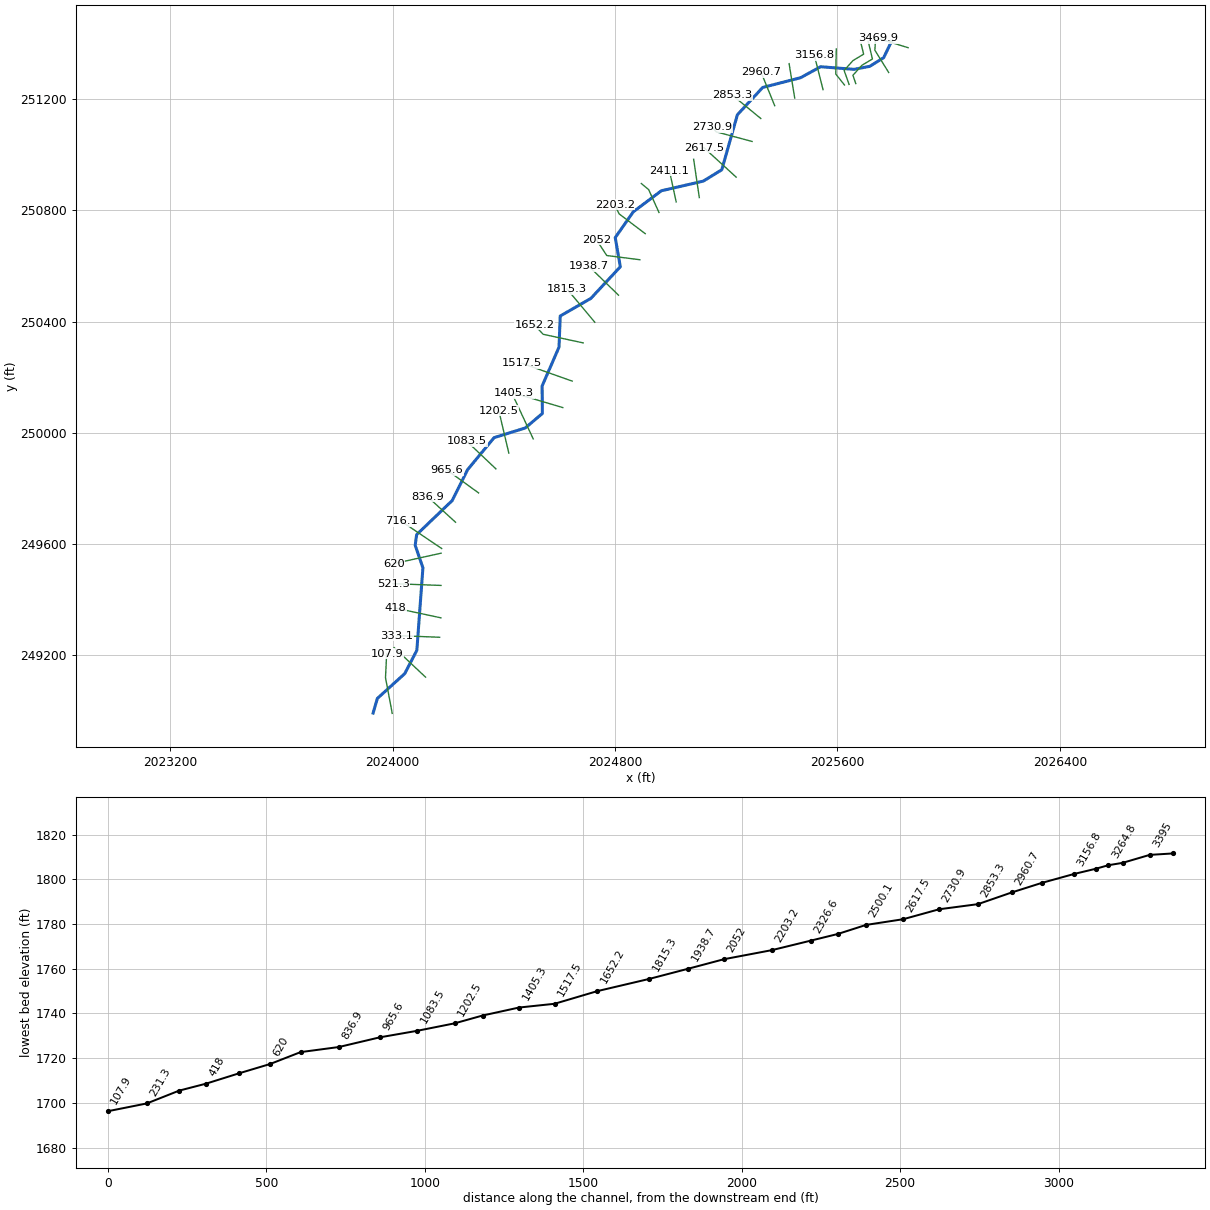
--- BIGCKTRIB.prj (project) ---

Proj Title=BIGCKTRIB
Current Plan=p01
Default Exp/Contr=0,0
English Units
Geom File=g01
Flow File=f01
Plan File=p01
BEGIN DESCRIPTION:
END DESCRIPTION:
DSS Export Rating Curves= 0
DSS Export Rating Curve Sorted= 0
DSS Export Volume Flow Curves= 0
DXF OffsetX= 0
DXF OffsetY= 0
DXF ScaleX= 0
DXF ScaleY= 0

--- BIGCKTRIB.p01 (plan) ---

Plan Title=Floodplain
Program Version=4.00
Geom File=g01
Flow File=f01
K Sum by GR=0
Std Step Tol=0.01
Critical Tol=0.01
Num of Std Step Trials=20
Max Error Tol=0.3
Flow Tol Ratio=0.001
Split Flow NTrial=30
Split Flow Tol=0.02
Split Flow Ratio=0.02
Log Output Level=0
Friction Slope Method=1
Unsteady Friction Slope Method=2
Unsteady Bridges Friction Slope Method=1
Global Log Level=0
CheckData=False
Run HTab=0
Run UNet=0
Run PostProcess=0
UNET Theta=0
UNET Theta Warmup=0
UNET ZTol=0
UNET ZSATol=0
UNET MxIter=0
UNET MaxInSteps=0
UNET DtIC=0
UNET DtMin=0
UNET MaxCRTS=0
UNET WFStab=0
UNET SFStab=0
UNET WFX=0
UNET SFX=0
UNET DSS MLevel=0
UNET DZMax Abort=0
UNET Convert EG Bridges=0
UNET Use Existing IB Tables=0
UNET Froude Limit=0
UNET Froude Power=0
Write IC File=0
Echo Input=False
Echo Output=False
Write Detailed=0

--- BIGCKTRIB.f01 (steady flow) ---

Flow Title=NFF Regression Equation
Program Version=4.10
Number of Profiles= 1
Profile Names=P100yr
River Rch & RM=BIGCKTRIB,Main            ,3469.9
 529.632
River Rch & RM=BIGCKTRIB,Main            ,1083.5
 559.515
River Rch & RM=BIGCKTRIB,Main            ,521.3
563.5125
Boundary for River Rch & Prof#=BIGCKTRIB,Main            , 1
Up Type= 0
Dn Type= 3
Dn Slope=0.03
DSS Import GetInterval= 0
DSS Import GetPeak= 0
DSS Import FillOption= 0

--- BIGCKTRIB.g01 (geometry) ---

Geom Title=USGS 1m DEM
Program Version=4.10

River Reach=BIGCKTRIB       ,Main
Reach XY= 30
     2025794.321      251407.887     2025766.201      251349.196
     2025715.771      251317.956     2025659.524      251307.277
      2025539.32      251316.647     2025467.424      251277.182
     2025330.986      251241.994     2025240.031      251144.014
     2025183.781       250945.97     2025117.445      250905.189
     2024966.403      250870.466     2024865.709      250794.946
     2024800.605      250702.064     2024818.834      250597.029
     2024712.931      250483.314     2024602.688      250419.946
     2024598.348      250307.967     2024537.584       250168.21
     2024538.452      250069.251      2024476.82      250017.168
     2024364.841      249982.446     2024269.355      249866.994
     2024214.113       249756.15     2024086.195      249633.487
     2024080.987      249595.293     2024108.747      249514.016
     2024086.956      249217.454     2024043.394      249133.541
     2023944.862      249044.253     2023929.582      248991.805

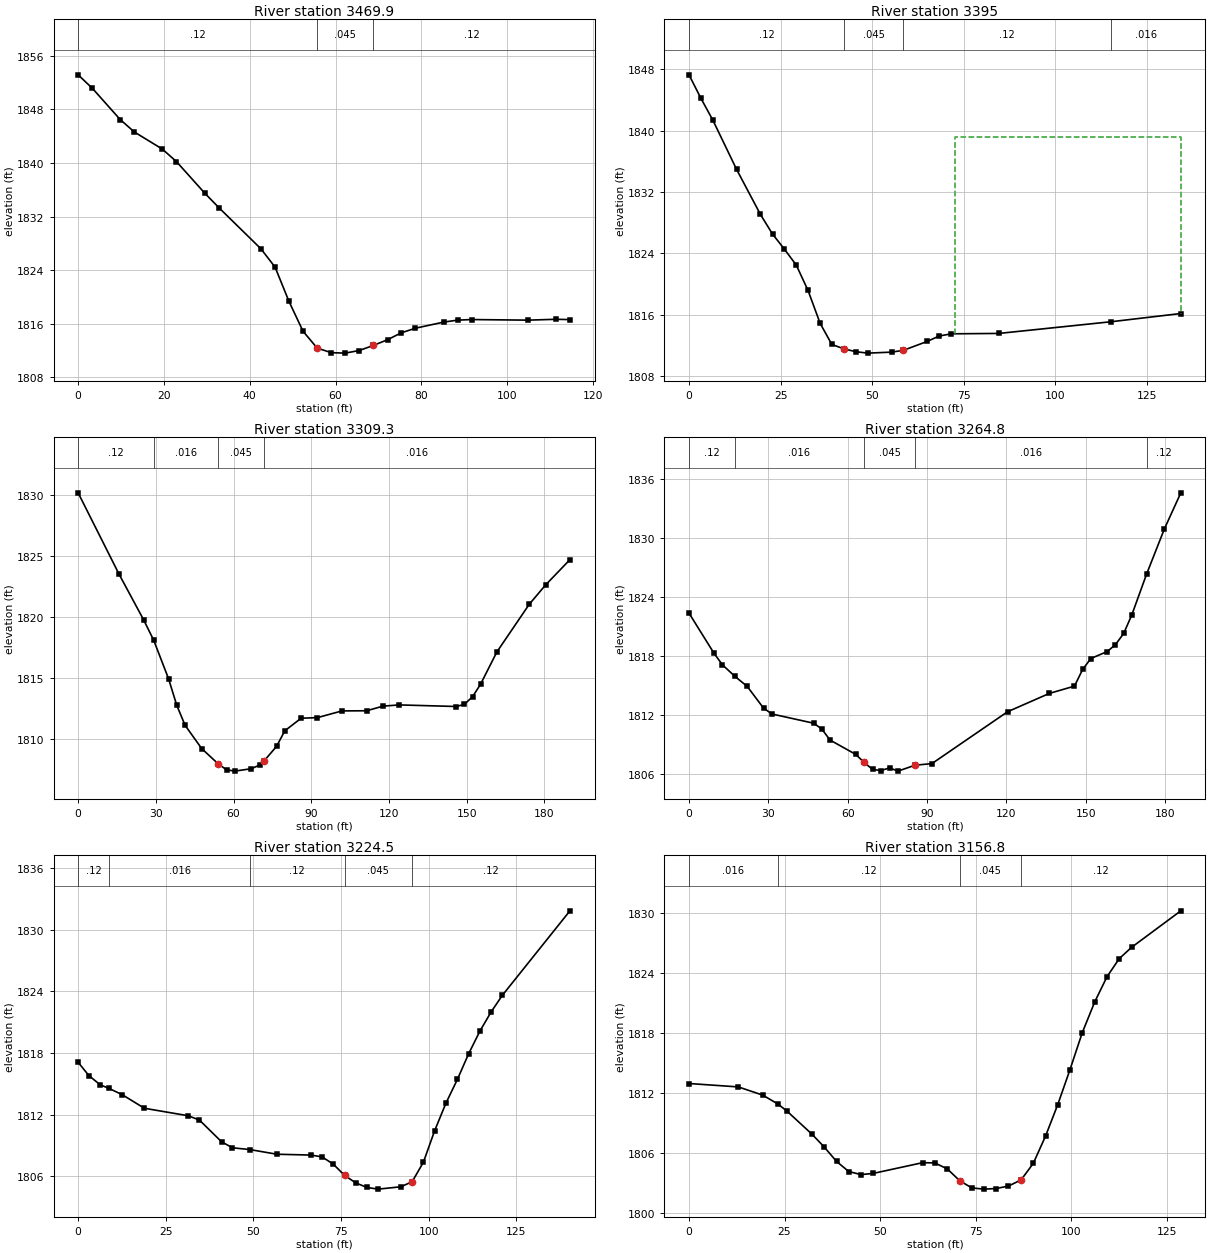
Type RM Length L Ch R = 1 ,3469.9  ,102.2,74.9,47.5
XS GIS Cut Line= 2
     2025854.059      251385.141     2025744.467      251418.778
#Sta/Elev= 26
       0 1853.14     3.3 1851.14     9.8 1846.47    13.1 1844.61    19.6 1842.07
    22.9  1840.2    29.5 1835.49    32.8 1833.32    42.6 1827.18    45.9 1824.44
    49.1 1819.38    52.4 1814.89    55.7 1812.37      59 1811.69    62.2 1811.62
    65.5 1812.01    68.8 1812.77    72.1 1813.62    75.3 1814.65    78.6 1815.34
    85.2 1816.25    88.4 1816.54    91.7 1816.63   104.8 1816.54   111.4 1816.67
   114.6 1816.62
#Mann= 3 ,-1 , 0
       0     .12       0    55.7    .045       0    68.8     .12       0
Bank Sta=55.7,68.8
XS Rating Curve= 0 ,0
Exp/Cntr=0.3,0.1

Type RM Length L Ch R = 1 ,3395    ,123.1,85.8,17.4
XS GIS Cut Line= 3
     2025784.098      251295.982     2025734.452       251376.18
     2025737.057       251416.11
#Sta/Elev= 22
       0 1847.28     3.2 1844.26     6.5 1841.37      13 1834.93    19.5 1829.06
    22.8  1826.5      26 1824.56    29.3 1822.44    32.5 1819.14    35.8 1814.85
      39 1812.09    42.3 1811.52    45.5 1811.15    48.8 1810.96    55.3 1811.09
    58.5 1811.32      65 1812.48    68.3 1813.19    71.6 1813.48    84.6 1813.53
   115.31815.059   134.3 1816.13
#Mann= 4 ,-1 , 0
       0     .12       0    42.3    .045       0    58.5     .12       0
   115.3    .016       0
#XS Ineff= 2 , 0
                           72.74         1839.18
Permanent Ineff=
       F       F
Bank Sta=42.3,58.5
XS Rating Curve= 0 ,0
Exp/Cntr=0.3,0.1

Type RM Length L Ch R = 1 ,3309.3  ,27.7,44.5,54.6
XS GIS Cut Line= 5
     2025665.716      251255.987     2025655.633      251285.989
     2025687.838      251321.752     2025725.772      251344.496
     2025710.328      251408.589
#Sta/Elev= 30
       0 1830.16    15.8  1823.5    25.3 1819.76   29.211818.078    34.9 1814.95
    38.1 1812.76    41.3 1811.13    47.7 1809.23    54.1 1807.97    57.3 1807.49
    60.5 1807.38    66.9 1807.58    70.2 1807.89    71.6 1808.17    76.6  1809.4
    79.8 1810.68    86.1 1811.71    92.4 1811.76   101.9 1812.31   111.4 1812.32
   117.7  1812.7     124  1812.8     146 1812.67   149.1 1812.84   152.3 1813.47
   155.4  1814.5   161.7 1817.14   174.2 1821.04   180.5 1822.62   189.9 1824.69
#Mann= 4 ,-1 , 0
       0     .12       0   29.21    .016       0    54.1    .045       0
    71.6    .016       0
Bank Sta=54.1,71.6
XS Rating Curve= 0 ,0
Exp/Cntr=0.3,0.1

Type RM Length L Ch R = 1 ,3264.8  ,34,40.3,76.2
XS GIS Cut Line= 5
     2025641.703      251253.047     2025623.949       251303.35
     2025656.154      251339.114     2025694.088      251361.857
     2025684.416      251400.885
#Sta/Elev= 30
       0 1822.36     9.4 1818.31    12.6 1817.13   17.311815.958      22 1814.93
    28.2 1812.72    31.4 1812.13    47.1  1811.2    50.2 1810.61    53.3 1809.49
      63 1808.04    66.2 1807.22    69.4 1806.51    72.6  1806.4    75.8 1806.67
      79 1806.34    85.4 1806.94    91.8  1807.1   120.4 1812.36   136.2 1814.22
   145.7 1814.96   148.8 1816.66   151.9 1817.76   158.1 1818.47   161.2 1819.17
   164.3  1820.3   167.4  1822.2  172.931826.299   179.7 1830.91   185.9 1834.56
#Mann= 5 ,-1 , 0
       0     .12       0   17.31    .016       0    66.2    .045       0
    85.4    .016       0  172.93     .12       0
Bank Sta=66.2,85.4
XS Rating Curve= 0 ,0
Exp/Cntr=0.3,0.1

Type RM Length L Ch R = 1 ,3224.5  ,64.8,67.7,77.6
XS GIS Cut Line= 3
     2025625.093      251251.013     2025593.827      251290.416
     2025595.732      251380.382
#Sta/Elev= 30
       0 1817.09     3.1 1815.78     6.3  1814.9    8.861814.537    12.6 1813.93
    18.9 1812.61    31.4 1811.88    34.6 1811.46    40.9 1809.35      44 1808.76
   49.031808.583    56.7 1808.13    66.4 1808.05    69.6 1807.87    72.8 1807.16
      76 1806.07    79.2 1805.34    82.4 1804.89    85.6 1804.73    92.1 1804.96
    95.3 1805.46    98.5 1807.36   101.7 1810.42   104.9 1813.09   108.2 1815.43
   111.4 1817.92   114.6 1820.12   117.8 1821.99     121 1823.61   140.3 1831.85
#Mann= 5 ,-1 , 0
       0     .12       0    8.86    .016       0   49.03     .12       0
      76    .045       0    95.3     .12       0
Bank Sta=76,95.3
XS Rating Curve= 0 ,0
Exp/Cntr=0.3,0.1

Type RM Length L Ch R = 1 ,3156.8  ,106.1,102.9,99.8
XS GIS Cut Line= 2
     2025548.069      251234.138     2025516.446      251358.871
#Sta/Elev= 30
       0 1812.98    12.9 1812.64    19.3 1811.82   23.261810.932    25.7  1810.2
    32.2 1807.91    35.4 1806.63    38.6  1805.2    41.8 1804.19      45 1803.88
    48.2    1804    61.1 1805.07    64.3 1805.05    67.6 1804.45    70.8 1803.28
      74 1802.55    77.2 1802.43    80.4 1802.49    83.6 1802.74    86.9 1803.35
    90.1 1805.01    93.3 1807.73    96.5 1810.88    99.7 1814.37   102.9 1818.05
   106.2 1821.16   109.4 1823.66   112.6 1825.46   115.8 1826.58   128.7 1830.23
#Mann= 4 ,-1 , 0
       0    .016       0   23.26     .12       0    70.8    .045       0
    86.9     .12       0
Bank Sta=70.8,86.9
XS Rating Curve= 0 ,0
Exp/Cntr=0.3,0.1

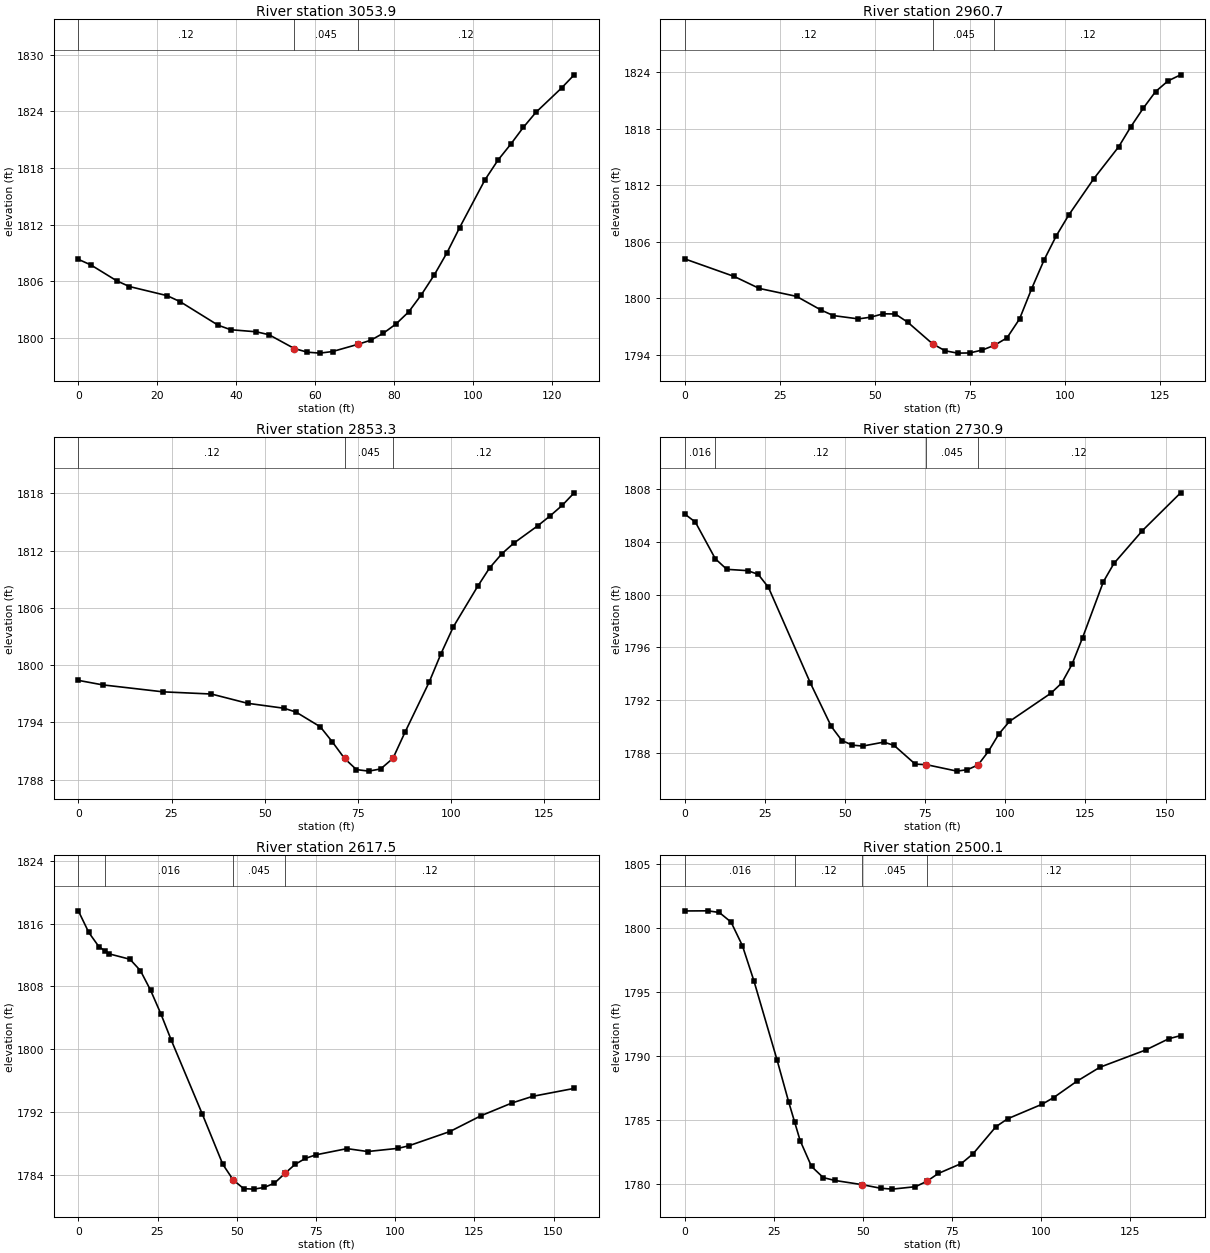
Type RM Length L Ch R = 1 ,3053.9  ,84.7,93.2,101.6
XS GIS Cut Line= 2
     2025446.174      251203.812     2025426.032      251327.764
#Sta/Elev= 30
       0 1808.33     3.2 1807.73     9.7 1806.06    12.9 1805.45    22.5 1804.48
    25.8 1803.84    35.4 1801.35    38.6 1800.87    45.1 1800.65    48.3 1800.34
    54.7 1798.88      58 1798.49    61.2 1798.39    64.4 1798.56    70.8 1799.32
    74.1 1799.76    77.3 1800.51    80.5 1801.49    83.7 1802.77    86.9 1804.58
    90.2  1806.7    93.4 1809.04    96.6  1811.7     103 1816.75   106.3 1818.84
   109.5 1820.51   112.7  1822.3   115.9  1823.9   122.4 1826.48   125.6 1827.88
#Mann= 3 ,-1 , 0
       0     .12       0    54.7    .045       0    70.8     .12       0
Bank Sta=54.7,70.8
XS Rating Curve= 0 ,0
Exp/Cntr=0.3,0.1

Type RM Length L Ch R = 1 ,2960.7  ,88.4,107.5,126.1
XS GIS Cut Line= 2
     2025374.109      251176.568     2025324.989      251297.429
#Sta/Elev= 30
       0 1804.18      13 1802.32    19.6 1801.05    29.4 1800.21    35.9 1798.75
    39.1 1798.17    45.7 1797.82    48.9    1798    52.2 1798.36    55.4 1798.34
    58.7 1797.46    65.2 1795.18    68.5 1794.44    71.8 1794.19      75 1794.21
    78.3 1794.52    81.5 1795.02    84.8 1795.81    88.1 1797.81    91.3 1801.03
    94.6  1804.1    97.8 1806.65   101.1 1808.86   107.6 1812.66   114.2 1816.07
   117.4  1818.2   120.7 1820.18   123.9 1821.92   127.2 1823.06   130.5  1823.7
#Mann= 3 ,-1 , 0
       0     .12       0    65.2    .045       0    81.5     .12       0
Bank Sta=65.2,81.5
XS Rating Curve= 0 ,0
Exp/Cntr=0.3,0.1

Type RM Length L Ch R = 1 ,2853.3  ,106.4,122.4,138.3
XS GIS Cut Line= 2
     2025324.252       251130.34     2025221.321      251214.614
#Sta/Elev= 26
       0 1798.41     6.5 1797.94    22.7 1797.21    35.7 1796.98    45.4 1796.01
    55.2 1795.49    58.4 1795.09    64.9 1793.55    68.1 1791.99    71.4 1790.24
    74.6 1789.07    77.9 1788.91    81.1 1789.14    84.4 1790.25    87.6 1792.96
    94.1 1798.22    97.3 1801.22   100.6 1804.02   107.1 1808.24   110.3 1810.17
   113.6 1811.66   116.8 1812.77   123.3 1814.61   126.5 1815.61   129.8 1816.73
     133 1818.04
#Mann= 3 ,-1 , 0
       0     .12       0    71.4    .045       0    84.4     .12       0
Bank Sta=71.4,84.4
XS Rating Curve= 0 ,0
Exp/Cntr=0.3,0.1

Type RM Length L Ch R = 1 ,2730.9  ,131.4,113.4,94.1
XS GIS Cut Line= 3
      2025292.76      251047.829     2025163.419      251082.551
     2025150.496       251098.86
#Sta/Elev= 30
       0 1806.11     3.3  1805.5    9.52 1802.72    13.1 1801.92    19.6 1801.82
    22.9 1801.54    26.1 1800.55    39.2 1793.29    45.7 1790.01      49 1788.94
    52.3 1788.59    55.5 1788.52    62.1 1788.82    65.3 1788.57    71.9 1787.15
    75.4 1787.11    84.9 1786.62    88.2 1786.73    91.5 1787.09    94.7 1788.11
      98 1789.44   101.3 1790.39   114.3 1792.54   117.6  1793.3   120.8 1794.71
   124.1 1796.73   130.6 1800.98   133.9 1802.37   142.8 1804.86   154.7 1807.72
#Mann= 4 ,-1 , 0
       0    .016       0    9.52     .12       0    75.4    .045       0
    91.5     .12       0
Bank Sta=75.4,91.5
XS Rating Curve= 0 ,0
Exp/Cntr=0.3,0.1

Type RM Length L Ch R = 1 ,2617.5  ,143,117.3,92.1
XS GIS Cut Line= 2
      2025235.55      250919.541     2025119.971      251024.993
#Sta/Elev= 30
       0 1817.62     3.3 1814.86     6.5 1813.05    8.481812.498     9.8 1812.13
    16.3 1811.45    19.6    1810    22.8 1807.51    26.1 1804.45    29.3 1801.18
    39.1 1791.76    45.6 1785.33    48.9 1783.33    52.2 1782.23    55.4 1782.17
    58.7 1782.39    61.9 1782.93    65.2 1784.17    68.4 1785.32    71.7 1786.09
      75 1786.54    84.8 1787.33    91.3 1786.96     101 1787.37   104.3 1787.69
   117.3 1789.51   127.1 1791.52   136.9 1793.15   143.4 1793.99   156.5    1795
#Mann= 4 ,-1 , 0
       0     .12       0    8.48    .016       0    48.9    .045       0
    65.2     .12       0
Bank Sta=48.9,65.2
XS Rating Curve= 0 ,0
Exp/Cntr=0.3,0.1

Type RM Length L Ch R = 1 ,2500.1  ,86.6,89,91.6
XS GIS Cut Line= 2
     2025102.993      250846.016     2025082.615      250983.773
#Sta/Elev= 30
       0 1801.32     6.5 1801.33     9.7  1801.2      13 1800.45    16.2  1798.6
    19.4 1795.88    25.9 1789.71    29.2  1786.4   30.891784.816    32.4  1783.4
    35.6 1781.38    38.9 1780.51    42.1 1780.29    49.8 1779.96      55 1779.68
    58.3 1779.61    64.8  1779.8      68 1780.22    71.2 1780.83    77.7 1781.61
      81 1782.37    87.4 1784.48    90.7  1785.1   100.4 1786.24   103.6 1786.75
   110.1 1788.02   116.6 1789.12   129.5 1790.47     136 1791.35   139.3 1791.59
#Mann= 4 ,-1 , 0
       0    .016       0   30.89     .12       0    49.8    .045       0
      68     .12       0
Bank Sta=49.8,68
XS Rating Curve= 0 ,0
Exp/Cntr=0.3,0.1

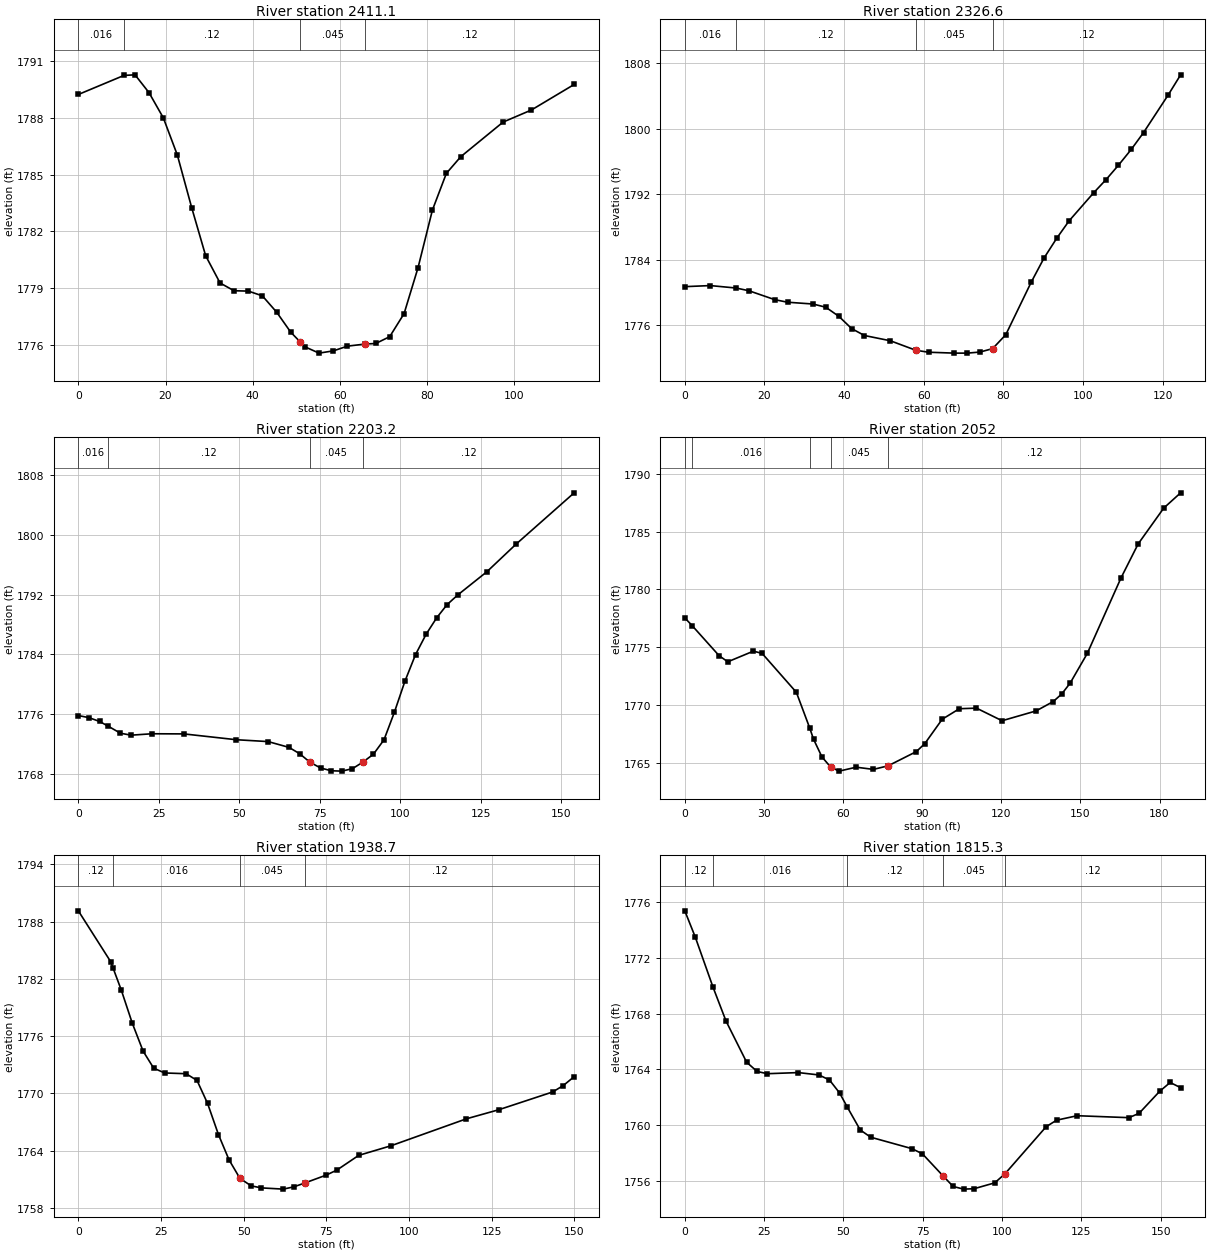
Type RM Length L Ch R = 1 ,2411.1  ,76.5,84.5,97.1
XS GIS Cut Line= 3
     2025019.838      250830.258     2024995.769      250941.347
     2024995.152      250942.057
#Sta/Elev= 30
       0 1789.24   10.471790.249      13 1790.28    16.2 1789.34    19.5    1788
    22.7 1786.04      26 1783.25    29.2 1780.71    32.5 1779.27    35.7 1778.86
      39 1778.84    42.2 1778.59    45.5 1777.72    48.7 1776.67    50.8 1776.17
      52 1775.89    55.2 1775.56    58.5 1775.68    61.7 1775.93    65.8 1776.04
    68.2 1776.07    71.4 1776.43    74.7 1777.65    77.9 1780.08    81.2 1783.13
    84.4 1785.07    87.7 1785.95    97.4 1787.78   103.9 1788.42   113.7 1789.77
#Mann= 4 ,-1 , 0
       0    .016       0   10.47     .12       0    50.8    .045       0
    65.8     .12       0
Bank Sta=50.8,65.8
XS Rating Curve= 0 ,0
Exp/Cntr=0.3,0.1

Type RM Length L Ch R = 1 ,2326.6  ,104.5,123.4,137
XS GIS Cut Line= 3
     2024957.826      250792.367     2024920.798      250874.652
     2024894.357      250896.495
#Sta/Elev= 30
       0 1780.72     6.4 1780.85   12.891780.551    16.1 1780.22    22.6 1779.13
    25.8 1778.82    32.2  1778.6    35.4 1778.21    38.7 1777.09    41.9  1775.6
    45.1 1774.76    51.6 1774.12      58 1772.96    61.2 1772.72    67.7 1772.61
    70.9 1772.61    74.1 1772.74    77.3 1773.16    80.6 1774.86      87 1781.28
    90.2 1784.21    93.4 1786.63    96.5 1788.75   102.7 1792.19   105.8 1793.79
   108.9 1795.54   112.1 1797.46   115.2 1799.52   121.4 1804.12   124.5 1806.56
#Mann= 4 ,-1 , 0
       0    .016       0   12.89     .12       0      58    .045       0
    77.3     .12       0
Bank Sta=58,77.3
XS Rating Curve= 0 ,0
Exp/Cntr=0.3,0.1

Type RM Length L Ch R = 1 ,2203.2  ,131.3,151.2,169.7
XS GIS Cut Line= 3
     2024908.437      250716.218     2024814.461      250787.412
     2024798.432      250819.893
#Sta/Elev= 30
       0 1775.78     3.3  1775.5     6.6 1774.99    9.321774.344    13.1 1773.41
    16.4 1773.15    22.9 1773.34    32.8 1773.32    49.1 1772.54      59 1772.29
    65.5 1771.51    68.8 1770.66      72 1769.52    75.3 1768.75    78.6 1768.38
    81.9 1768.33    85.2 1768.66    88.4 1769.53    91.7 1770.59      95 1772.53
    98.2 1776.19   101.5 1780.38   104.8 1783.95   108.1 1786.69   111.4  1788.9
   114.6 1790.65   117.9 1791.94     127 1795.07     136 1798.74   154.1 1805.64
#Mann= 4 ,-1 , 0
       0    .016       0    9.32     .12       0      72    .045       0
    88.4     .12       0
Bank Sta=72,88.4
XS Rating Curve= 0 ,0
Exp/Cntr=0.3,0.1

Type RM Length L Ch R = 1 ,2052    ,138,113.3,88.8
XS GIS Cut Line= 3
     2024889.432      250622.337     2024770.075      250637.528
     2024732.995      250694.168
#Sta/Elev= 30
       0 1777.53    2.761776.866      13 1774.26    16.3 1773.73      26 1774.65
    29.3 1774.46    42.3 1771.09   47.381767.991    48.8 1767.04      52  1765.5
    55.3 1764.62    58.5 1764.27      65 1764.61    71.5 1764.42    77.1 1764.73
    87.8 1765.96      91 1766.65    97.6 1768.76   104.1 1769.67   110.6 1769.72
   120.3 1768.63   133.2 1769.48   139.7 1770.29   142.9 1770.94   146.1 1771.88
   152.6 1774.45   165.4 1780.99   171.9 1783.93   181.6 1787.03     188 1788.35
#Mann= 5 ,-1 , 0
       0     .12       0    2.76    .016       0   47.38     .12       0
    55.3    .045       0    77.1     .12       0
Bank Sta=55.3,77.1
XS Rating Curve= 0 ,0
Exp/Cntr=0.3,0.1

Type RM Length L Ch R = 1 ,1938.7  ,126.5,123.4,119.2
XS GIS Cut Line= 2
     2024812.286      250494.965     2024704.878      250599.654
#Sta/Elev= 28
       0 1789.12     9.8 1783.79   10.521783.122      13 1780.82    16.3 1777.38
    19.6 1774.43    22.8 1772.65    26.1 1772.15    32.6 1772.07    35.9 1771.37
    39.1 1768.96    42.4 1765.69    45.6 1763.05    48.9 1761.11    52.3 1760.33
    55.4 1760.12      62 1759.99    65.2 1760.23    68.5 1760.63      75 1761.46
    78.2 1761.98    84.8 1763.52    94.6 1764.53   117.4 1767.35   127.2  1768.3
   143.5 1770.16   146.7 1770.83     150 1771.76
#Mann= 4 ,-1 , 0
       0     .12       0   10.52    .016       0    48.9    .045       0
    68.5     .12       0
Bank Sta=48.9,68.5
XS Rating Curve= 0 ,0
Exp/Cntr=0.3,0.1

Type RM Length L Ch R = 1 ,1815.3  ,138.6,163.1,187.6
XS GIS Cut Line= 2
     2024727.132      250397.554     2024626.801      250517.343
#Sta/Elev= 30
       0 1775.36     3.3 1773.48    8.881769.899      13 1767.46    19.5 1764.51
    22.8 1763.85      26 1763.69    35.8 1763.77    42.3  1763.6    45.6 1763.24
    48.8 1762.31   51.211761.302    55.3 1759.66    58.6 1759.14    71.6 1758.32
    74.9 1757.95    81.4 1756.37    84.6 1755.61    87.9 1755.42    91.2 1755.45
    97.7 1755.87   100.9 1756.51   113.9 1759.89   117.2 1760.36   123.7 1760.68
     140 1760.54   143.2 1760.85   149.7 1762.43     153 1763.06   156.3 1762.69
#Mann= 5 ,-1 , 0
       0     .12       0    8.88    .016       0   51.21     .12       0
    81.4    .045       0   100.9     .12       0
Bank Sta=81.4,100.9
XS Rating Curve= 0 ,0
Exp/Cntr=0.3,0.1

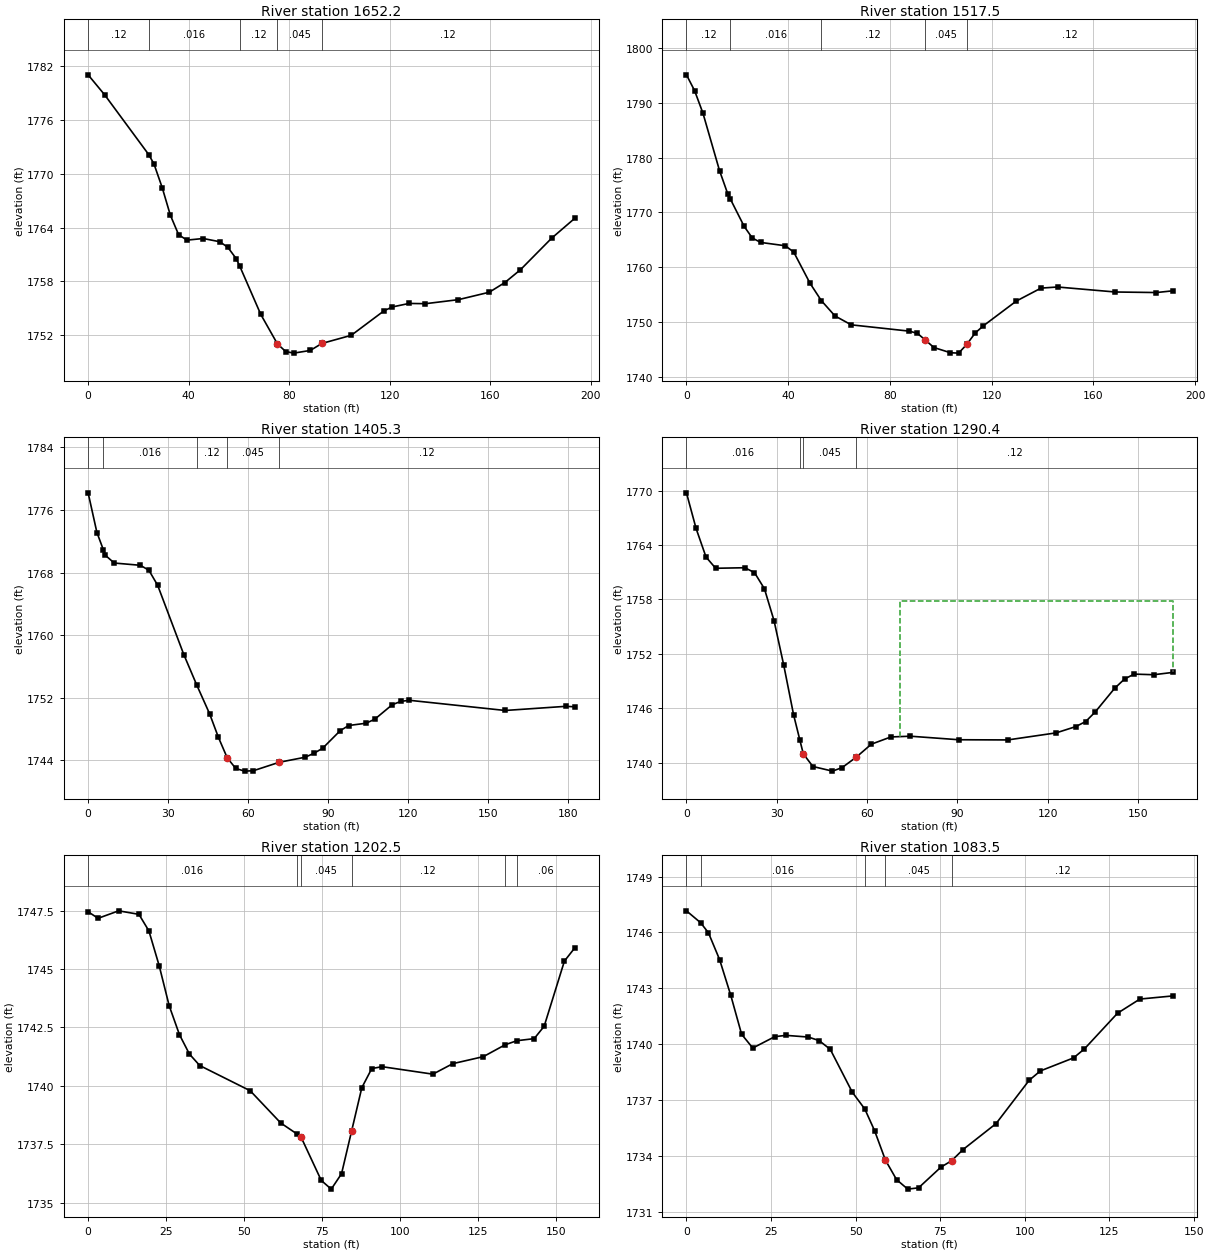
Type RM Length L Ch R = 1 ,1652.2  ,139.1,134.7,130.6
XS GIS Cut Line= 3
     2024685.038      250323.334     2024541.024      250354.252
     2024509.575      250388.291
#Sta/Elev= 30
       0 1781.06     6.6 1778.82   24.131772.145    26.2 1771.11    29.5 1768.44
    32.7  1765.4      36 1763.21    39.3  1762.6    45.8 1762.78    52.4 1762.42
    55.6 1761.79    58.9 1760.54   60.371759.667    68.7  1754.3    75.3 1751.02
    78.6 1750.16    81.8 1749.98    88.4 1750.28      93 1751.06   104.7 1751.97
   117.8 1754.72   121.1 1755.14   127.7 1755.53   134.2  1755.5   147.3 1755.95
   159.6 1756.78   165.8 1757.86     172 1759.29   184.4 1762.81   193.6 1765.03
#Mann= 5 ,-1 , 0
       0     .12       0   24.13    .016       0   60.37     .12       0
    75.3    .045       0      93     .12       0
Bank Sta=75.3,93
XS Rating Curve= 0 ,0
Exp/Cntr=0.3,0.1

Type RM Length L Ch R = 1 ,1517.5  ,110.5,112.1,112.3
XS GIS Cut Line= 2
     2024645.873       250185.72     2024465.567      250249.699
#Sta/Elev= 30
       0 1795.08     3.2  1792.2     6.5 1788.07      13 1777.62    16.2 1773.42
   17.271772.421    22.7 1767.43    25.9 1765.31    29.2 1764.51    38.9  1763.9
    42.2 1762.73    48.6 1757.05   53.031753.897    58.4  1751.1    64.8 1749.48
    87.6 1748.33    90.8 1747.93    93.9 1746.71    97.3 1745.34   103.8 1744.39
     107 1744.32   110.2  1745.9   113.5 1747.98   116.7 1749.29   129.7 1753.82
   139.4 1756.18   145.9 1756.38   168.6 1755.47   184.8 1755.37   191.3 1755.69
#Mann= 5 ,-1 , 0
       0     .12       0   17.27    .016       0   53.03     .12       0
    93.9    .045       0   110.2     .12       0
Bank Sta=93.9,110.2
XS Rating Curve= 0 ,0
Exp/Cntr=0.3,0.1

Type RM Length L Ch R = 1 ,1405.3  ,146.4,114.9,83.9
XS GIS Cut Line= 2
     2024612.023      250090.549     2024436.965      250142.445
#Sta/Elev= 30
       0  1778.2     3.3 1773.13    5.771770.876     6.5 1770.21     9.8 1769.23
    19.6 1768.94    22.8 1768.31    26.1 1766.38    35.9 1757.54   40.821753.598
    45.6 1749.96    48.9 1746.95    52.2 1744.34    55.4 1742.98    58.7 1742.64
      62 1742.69    71.7 1743.77    81.5 1744.42    84.8 1744.93      88 1745.56
    94.6 1747.81    97.8 1748.47   104.3 1748.76   107.6 1749.28   114.1 1751.12
   117.4 1751.56   120.6 1751.69   156.5 1750.39   179.3 1750.92   182.6 1750.86
#Mann= 5 ,-1 , 0
       0     .12       0    5.77    .016       0   40.82     .12       0
    52.2    .045       0    71.7     .12       0
Bank Sta=52.2,71.7
XS Rating Curve= 0 ,0
Exp/Cntr=0.3,0.1

Type RM Length L Ch R = 1 ,1290.4  ,95.4,87.9,79.9
XS GIS Cut Line= 2
     2024505.686      249977.702     2024437.327      250124.187
#Sta/Elev= 30
       0 1769.76     3.2 1765.83     6.5 1762.68     9.7 1761.44    19.4  1761.5
    22.6 1760.96    25.9 1759.18    29.1 1755.65    32.3 1750.78    35.6 1745.26
   37.661742.505    38.8 1740.98      42 1739.58    48.5 1739.07    51.7 1739.46
    56.4 1740.61    61.4 1742.04    67.9 1742.84    74.4 1742.92    90.5 1742.53
   106.7 1742.51   122.8 1743.29   129.3 1743.98   132.6 1744.54   135.8 1745.61
   142.2  1748.2   145.5 1749.23   148.7 1749.77   155.2  1749.7   161.6 1749.96
#Mann= 4 ,-1 , 0
       0    .016       0   37.66     .12       0    38.8    .045       0
    56.4     .12       0
#XS Ineff= 2 , 0
                           71.05         1757.86
Permanent Ineff=
       F       F
Bank Sta=38.8,56.4
XS Rating Curve= 0 ,0
Exp/Cntr=0.3,0.1

Type RM Length L Ch R = 1 ,1202.5  ,96.9,119,140.8
XS GIS Cut Line= 2
     2024417.796      249926.704     2024381.988      250078.614
#Sta/Elev= 30
       0 1747.45     3.2 1747.17     9.8 1747.49    16.3 1747.34    19.5 1746.63
    22.8 1745.14      26 1743.43    29.3 1742.19    32.5 1741.36    35.8 1740.87
      52 1739.79    61.8 1738.41   66.971737.943    68.3 1737.81    74.8 1735.95
      78 1735.58    81.3 1736.24    84.5 1738.05    87.8 1739.92      91 1740.74
    94.3 1740.82   110.6  1740.5     117 1740.95   126.8 1741.25   133.81741.759
  137.561741.932   143.1 1742.02   146.3 1742.55   152.8 1745.34   156.1  1745.9
#Mann= 6 ,-1 , 0
       0    .016       0   66.97     .12       0    68.3    .045       0
    84.5     .12       0   133.8    .016       0  137.56     .06       0
Bank Sta=68.3,84.5
XS Rating Curve= 0 ,0
Exp/Cntr=0.3,0.1

Type RM Length L Ch R = 1 ,1083.5  ,112.8,117.9,122.8
XS GIS Cut Line= 2
     2024371.319      249870.094     2024266.971      249969.022
#Sta/Elev= 30
       0 1747.16     4.21746.519     6.5 1745.98     9.8 1744.54    13.1 1742.62
    16.3 1740.53    19.6 1739.79    26.1  1740.4    29.4 1740.47      36 1740.38
    39.2 1740.19    42.5 1739.72      49 1737.42   52.721736.511    55.6 1735.35
    58.8 1733.77    62.1 1732.72    65.4 1732.21    68.6 1732.28    75.2 1733.39
    78.4 1733.74    81.7 1734.33    91.5 1735.73   101.3 1738.06   104.6 1738.56
   114.4 1739.26   117.6 1739.74   127.4 1741.66     134 1742.42   143.8 1742.59
#Mann= 5 ,-1 , 0
       0     .12       0     4.2    .016       0   52.72     .12       0
    58.8    .045       0    78.4     .12       0
Bank Sta=58.8,78.4
XS Rating Curve= 0 ,0
Exp/Cntr=0.3,0.1

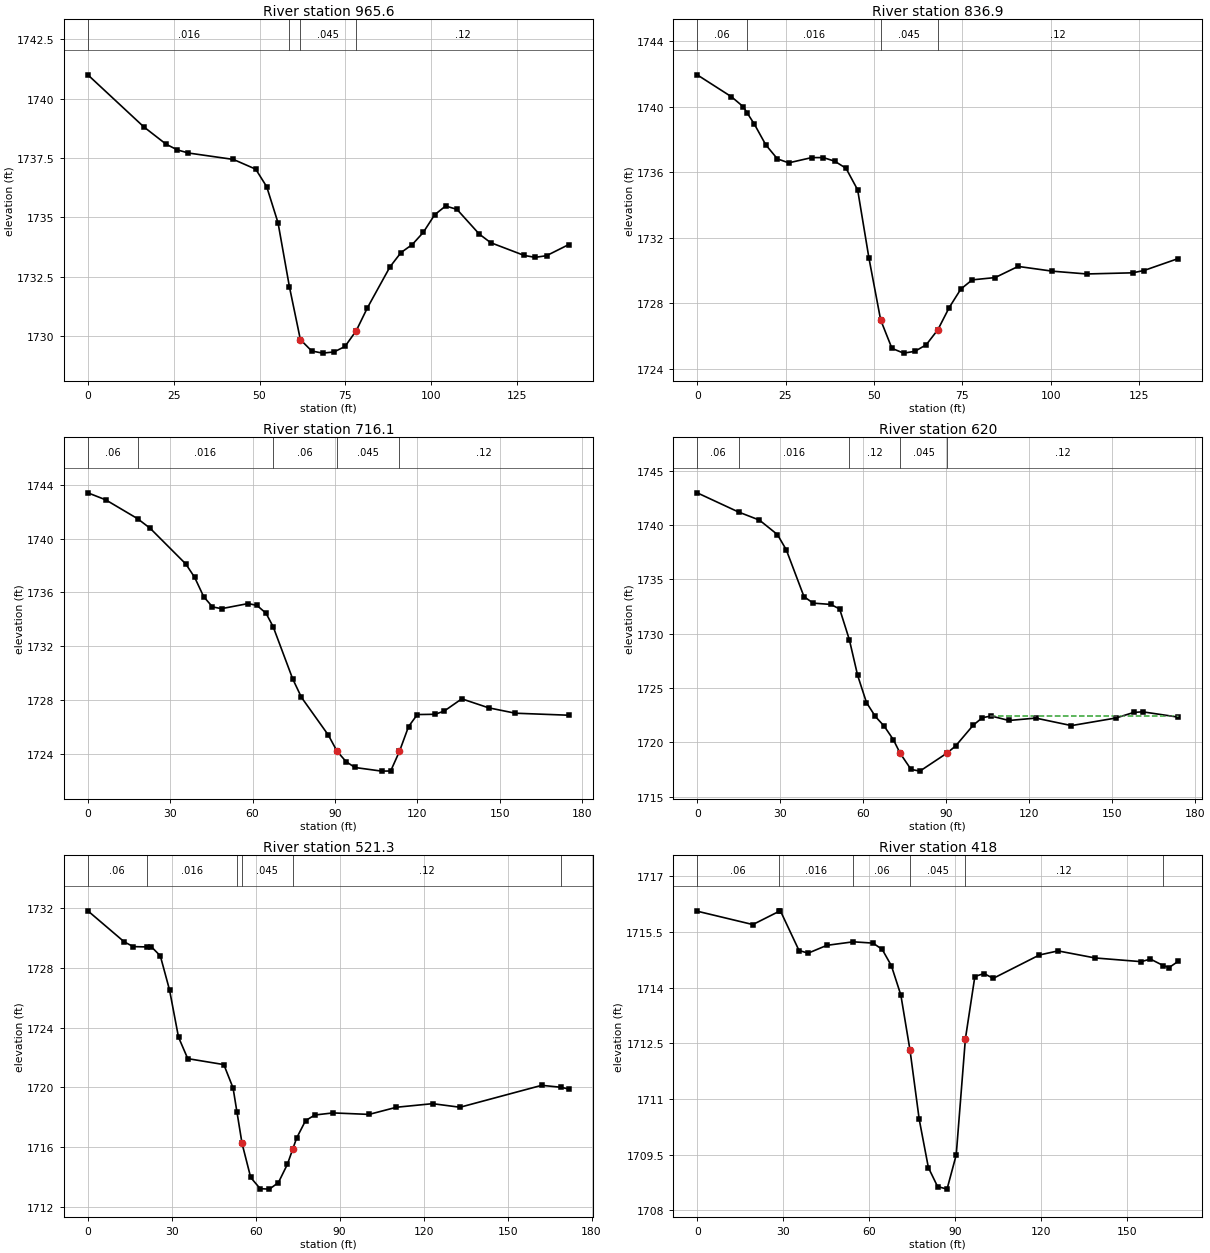
Type RM Length L Ch R = 1 ,965.6   ,132.6,128.7,124.2
XS GIS Cut Line= 2
     2024308.973      249783.648     2024195.453      249865.732
#Sta/Elev= 30
       0    1741    16.3 1738.81    22.8 1738.08    26.1 1737.84    29.3 1737.71
    42.4 1737.44    48.9 1737.03    52.1 1736.29    55.4 1734.77    58.7 1732.09
    61.9 1729.86    65.2 1729.38    68.4 1729.29    71.7 1729.34    74.9 1729.57
    78.2 1730.24    81.4 1731.19      88 1732.92    91.2 1733.52    94.5 1733.86
    97.7 1734.37     101 1735.11   104.2 1735.48   107.5 1735.34     114  1734.3
   117.3 1733.94   127.1  1733.4   130.3 1733.32   133.6 1733.39   140.1 1733.86
#Mann= 4 ,-1 , 0
       0    .016       0    58.7     .12       0    61.9    .045       0
    78.2     .12       0
Bank Sta=61.9,78.2
XS Rating Curve= 0 ,0
Exp/Cntr=0.3,0.1

Type RM Length L Ch R = 1 ,836.9   ,115.2,120.8,126.2
XS GIS Cut Line= 2
     2024226.143       249678.12     2024125.581      249769.889
#Sta/Elev= 30
       0 1741.95     9.7 1740.61      13 1740.01   14.181739.612    16.2 1738.93
    19.4 1737.68    22.7 1736.82    25.9 1736.58    32.4  1736.9    35.7  1736.9
    38.9 1736.68    42.1 1736.25    45.4 1734.93    48.6 1730.76    51.9    1727
    55.1 1725.26    58.4 1724.97    61.6 1725.08    64.8 1725.48    68.1  1726.4
    71.3 1727.75    74.6 1728.88    77.8 1729.44    84.3 1729.58    90.8 1730.26
   100.5 1729.97   110.2  1729.8   123.2 1729.87   126.4 1730.01   136.1 1730.74
#Mann= 4 ,-1 , 0
       0     .06       0   14.18    .016       0    51.9    .045       0
    68.1     .12       0
Bank Sta=51.9,68.1
XS Rating Curve= 0 ,0
Exp/Cntr=0.3,0.1

Type RM Length L Ch R = 1 ,716.1   ,65.5,96.2,126.9
XS GIS Cut Line= 2
     2024176.346      249583.552     2024031.196      249681.609
#Sta/Elev= 30
       0  1743.4     6.5 1742.88    18.11741.478    22.7 1740.76    35.7  1738.1
    38.9 1737.11    42.2 1735.67    45.4 1734.91    48.7 1734.78    58.4 1735.16
    61.6 1735.02    64.9 1734.44   67.511733.429    74.6 1729.56    77.8 1728.18
    87.6 1725.37    90.8 1724.16    94.1 1723.39    97.3 1722.96     107 1722.69
   110.3  1722.7   113.5 1724.16   116.8    1726     120  1726.9   126.5 1726.92
   129.8 1727.16   136.2 1728.07     146  1727.4   155.7    1727   175.2 1726.85
#Mann= 5 ,-1 , 0
       0     .06       0    18.1    .016       0   67.51     .06       0
    90.8    .045       0   113.5     .12       0
Bank Sta=90.8,113.5
XS Rating Curve= 0 ,0
Exp/Cntr=0.3,0.1

Type RM Length L Ch R = 1 ,620     ,107.7,98.7,88.5
XS GIS Cut Line= 2
     2024174.114      249566.778     2024004.284      249529.292
#Sta/Elev= 30
       0 1742.97   14.971741.201    22.5 1740.46      29 1739.13    32.2 1737.73
    38.6 1733.42    41.9 1732.82    48.3  1732.7    51.5 1732.28      551729.461
      58 1726.17    61.2 1723.67    64.4 1722.39    67.6  1721.5    70.9 1720.26
    73.4 1718.99    77.3 1717.52    80.5 1717.36    90.2    1719    93.4 1719.67
    99.8 1721.59   103.1 1722.28   106.3 1722.43   112.7 1722.02   122.4 1722.24
   135.3 1721.55   151.4 1722.25   157.8 1722.76     161 1722.82   173.9 1722.33
#Mann= 5 ,-1 , 0
       0     .06       0   14.97    .016       0      55     .12       0
    73.4    .045       0    90.2     .12       0
#XS Ineff= 2 , 0
                             106         1722.42
Permanent Ineff=
       F       F
Bank Sta=73.4,90.2
XS Rating Curve= 0 ,0
Exp/Cntr=0.3,0.1

Type RM Length L Ch R = 1 ,521.3   ,109.8,103.3,96.7
XS GIS Cut Line= 2
     2024173.639      249450.834     2024001.879       249457.17
#Sta/Elev= 30
       0 1731.83      13 1729.75    16.2 1729.43   21.03 1729.41    22.7 1729.42
    25.9 1728.81    29.2 1726.52    32.4 1723.36    35.7 1721.92    48.6 1721.52
    51.9 1719.95   53.271718.362    55.1 1716.24    58.2 1713.95    61.6  1713.2
    64.9 1713.17    68.1 1713.61    71.3 1714.83    73.2 1715.84    74.6 1716.59
    77.8 1717.76    81.1 1718.14    87.6 1718.28   100.5 1718.18   110.3 1718.66
   123.2  1718.9     133 1718.66   162.2 1720.13  169.06    1720   171.9 1719.88
#Mann= 6 ,-1 , 0
       0     .06       0   21.03    .016       0   53.27     .12       0
    55.1    .045       0    73.2     .12       0  169.06     .06       0
Bank Sta=55.1,73.2
XS Rating Curve= 0 ,0
Exp/Cntr=0.3,0.1

Type RM Length L Ch R = 1 ,418     ,78.3,84.9,91.1
XS GIS Cut Line= 2
     2024173.623      249334.249     2024009.631      249369.332
#Sta/Elev= 30
       0 1716.06    19.4  1715.7   28.471716.053      29 1716.07    35.5    1715
    38.7 1714.93    45.2 1715.14   54.421715.235    61.3  1715.2    64.5 1715.03
    67.7 1714.59      71  1713.8    74.2 1712.31    77.4 1710.45    80.6 1709.15
    83.8 1708.64    87.1 1708.57    90.3 1709.49    93.5 1712.62    96.8  1714.3
     100 1714.38   103.2 1714.25   119.3 1714.88   125.8 1714.99   138.7  1714.8
   154.8  1714.7     158 1714.77  162.471714.595   164.5 1714.54   167.7 1714.71
#Mann= 6 ,-1 , 0
       0     .06       0   28.47    .016       0   54.42     .06       0
    74.2    .045       0    93.5     .12       0  162.47     .06       0
Bank Sta=74.2,93.5
XS Rating Curve= 0 ,0
Exp/Cntr=0.3,0.1

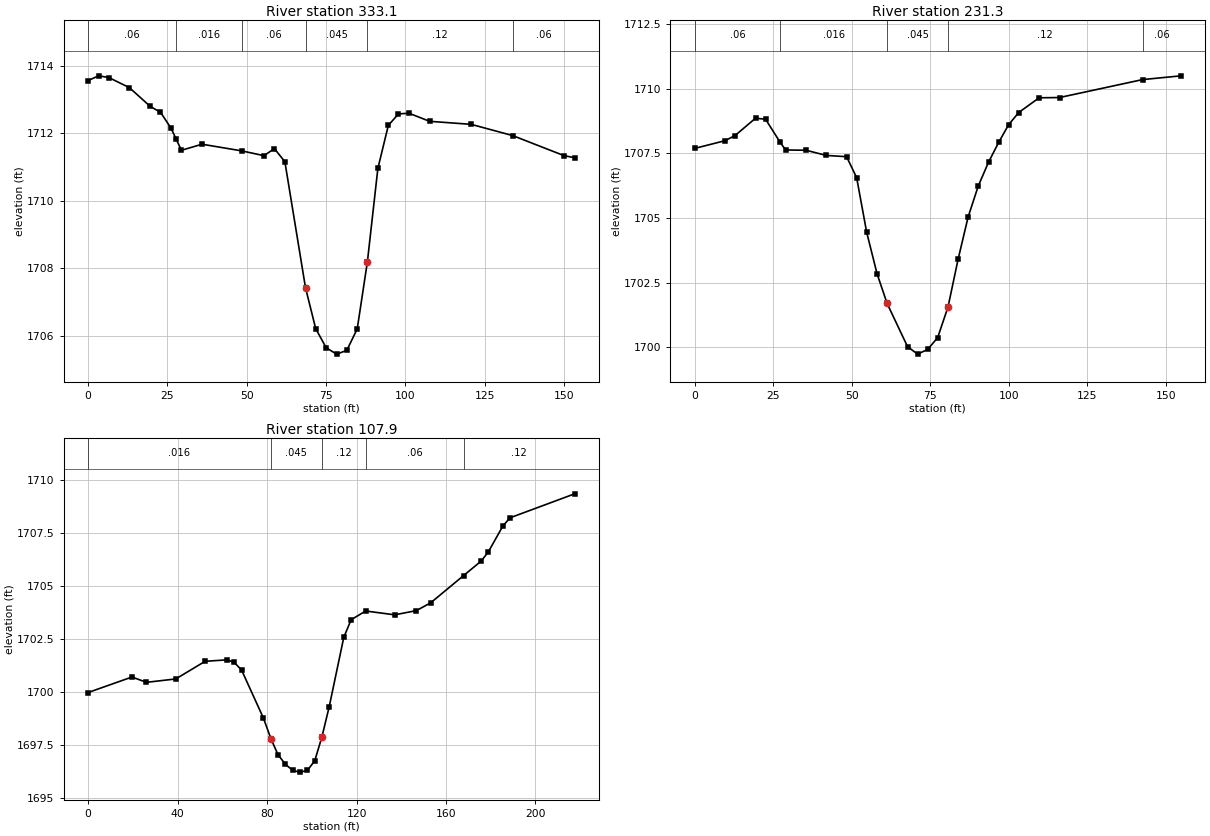
Type RM Length L Ch R = 1 ,333.1   ,128.9,101.8,74.6
XS GIS Cut Line= 2
     2024168.873      249264.313     2024015.728      249270.532
#Sta/Elev= 30
       0 1713.57     3.3 1713.71     6.5 1713.66      13 1713.36    19.6  1712.8
    22.8 1712.63    26.1 1712.16    27.7 1711.84    29.4  1711.5    35.9 1711.68
    48.51711.481    55.4 1711.34    58.7 1711.55      62 1711.16    68.5 1707.42
    71.7 1706.21      75 1705.64    78.3 1705.45    81.5 1705.56    84.8  1706.2
      88 1708.19    91.3 1710.96    94.6 1712.24    97.8 1712.58   101.1  1712.6
   107.6 1712.36   120.7 1712.27  133.761711.937     150 1711.34   153.3 1711.28
#Mann= 6 ,-1 , 0
       0     .06       0    27.7    .016       0    48.5     .06       0
    68.5    .045       0      88     .12       0  133.76     .06       0
Bank Sta=68.5,88
XS Rating Curve= 0 ,0
Exp/Cntr=0.3,0.1

Type RM Length L Ch R = 1 ,231.3   ,151.1,123.4,94.1
XS GIS Cut Line= 2
     2024118.238      249120.982     2024005.339      249226.982
#Sta/Elev= 30
       0 1707.69     9.7 1707.99    12.9 1708.19    19.4 1708.86    22.6 1708.82
   27.261707.924      29 1707.63    35.5 1707.62    41.9 1707.42    48.4 1707.37
    51.6 1706.56    54.8 1704.44    58.1 1702.84    61.3 1701.69    67.8 1700.02
      71 1699.73    74.2 1699.91    77.4 1700.37    80.7 1701.56    83.9  1703.4
    87.1 1705.04    90.3 1706.23    93.6 1707.16    96.8 1707.92     100 1708.61
   103.2 1709.08   109.7 1709.65   116.2 1709.66  142.631710.354   154.9  1710.5
#Mann= 5 ,-1 , 0
       0     .06       0   27.26    .016       0    61.3    .045       0
    80.7     .12       0  142.63     .06       0
Bank Sta=61.3,80.7
XS Rating Curve= 0 ,0
Exp/Cntr=0.3,0.1

Type RM Length L Ch R = 1 ,107.9   ,62.4,107.9,155.3
XS GIS Cut Line= 3
     2023998.393      248990.594     2023974.183      249119.009
     2023978.334      249205.757
#Sta/Elev= 30
       0 1699.98    19.6 1700.71    26.1 1700.46    39.2 1700.62    52.3 1701.45
    62.1 1701.52    65.3  1701.4    68.6 1701.04    78.4 1698.77    81.7 1697.81
    84.9 1697.05    88.2  1696.6    91.5 1696.31    94.7 1696.23      98 1696.31
   101.3 1696.76   104.5 1697.88   107.8 1699.32   114.3 1702.58   117.6 1703.41
  124.09 1703.82   137.1 1703.64   146.8 1703.84   153.2 1704.21  167.831705.487
   175.7 1706.17   178.9  1706.6   185.4 1707.82   188.6 1708.21   217.5 1709.34
#Mann= 5 ,-1 , 0
       0    .016       0    81.7    .045       0   104.5     .12       0
  124.09     .06       0  167.83     .12       0
Bank Sta=81.7,104.5
XS Rating Curve= 0 ,0
Exp/Cntr=0.3,0.1

Chan Stop Cuts=-1
Use User Specified Reach Order=0
Composite Channel Slope=5